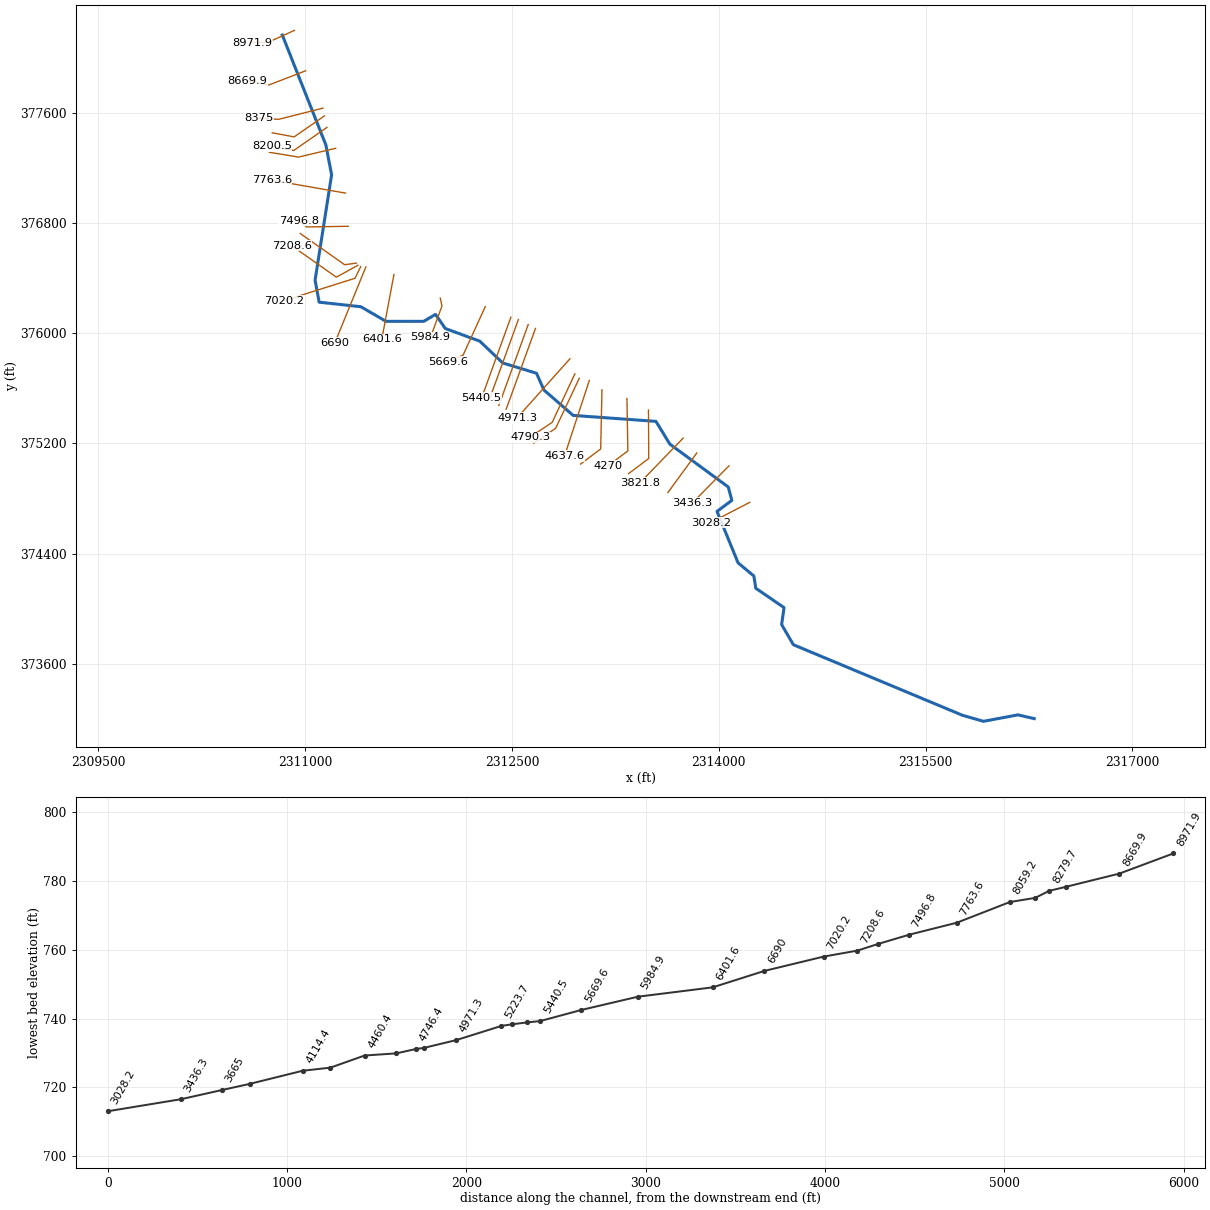
--- ROCKGAPRUN.prj (project) ---

Proj Title=ROCKGAPRUN
Current Plan=p01
Default Exp/Contr=0,0
English Units
Geom File=g01
Flow File=f01
Plan File=p01
BEGIN DESCRIPTION:
END DESCRIPTION:
DSS Export Rating Curves= 0
DSS Export Rating Curve Sorted= 0
DSS Export Volume Flow Curves= 0
DXF OffsetX= 0
DXF OffsetY= 0
DXF ScaleX= 0
DXF ScaleY= 0

--- ROCKGAPRUN.p01 (plan) ---

Plan Title=Floodplain
Program Version=4.00
Geom File=g01
Flow File=f01
K Sum by GR=0
Std Step Tol=0.01
Critical Tol=0.01
Num of Std Step Trials=20
Max Error Tol=0.3
Flow Tol Ratio=0.001
Split Flow NTrial=30
Split Flow Tol=0.02
Split Flow Ratio=0.02
Log Output Level=0
Friction Slope Method=1
Unsteady Friction Slope Method=2
Unsteady Bridges Friction Slope Method=1
Global Log Level=0
CheckData=False
Run HTab=0
Run UNet=0
Run PostProcess=0
UNET Theta=0
UNET Theta Warmup=0
UNET ZTol=0
UNET ZSATol=0
UNET MxIter=0
UNET MaxInSteps=0
UNET DtIC=0
UNET DtMin=0
UNET MaxCRTS=0
UNET WFStab=0
UNET SFStab=0
UNET WFX=0
UNET SFX=0
UNET DSS MLevel=0
UNET DZMax Abort=0
UNET Convert EG Bridges=0
UNET Use Existing IB Tables=0
UNET Froude Limit=0
UNET Froude Power=0
Write IC File=0
Echo Input=False
Echo Output=False
Write Detailed=0

--- ROCKGAPRUN.f01 (steady flow) ---

Flow Title=NFF Regression Equation
Program Version=4.00
Number of Profiles=1
Profile Names=P100yr
River Rch & RM=ROCKGAPRUN,Main      ,8971.9
792.5536
River Rch & RM=ROCKGAPRUN,Main      ,7020.2
805.6024
River Rch & RM=ROCKGAPRUN,Main      ,6690
1041.589
River Rch & RM=ROCKGAPRUN,Main      ,3821.8
1103.126
River Rch & RM=ROCKGAPRUN,Main      ,3436.3
1293.657
River Rch & RM=ROCKGAPRUN,Main      ,567.7
1415.612
River Rch & RM=ROCKGAPRUN,Main      ,150.5
1418.082
Boundary for River Rch & Prof#=ROCKGAPRUN,Main      ,1
Up Type=0
Dn Type=3
Dn Slope=0.004625

--- ROCKGAPRUN.g01 (geometry) ---

Geom Title=USGS 10m DEM
Program Version=4.10

River Reach=ROCKGAPRUN      ,Main
Reach XY= 30
     2310834.234      378162.425     2311150.207       377365.55
     2311191.874      377148.536     2311072.082      376384.647
     2311101.596      376224.925     2311403.679      376191.939
     2311585.971      376086.036     2311860.276      376086.036
     2311945.346      376136.383     2312016.526      376033.953
     2312266.526      375941.939     2312433.193      375783.952
     2312677.984        375709.3     2312731.804      375587.772
      2312943.61      375403.744     2313544.304      375360.341
     2313644.999      375195.411      2314068.61      374884.647
     2314094.651      374787.425     2313987.012      374707.564
      2314139.79        374334.3     2314254.373      374238.814
     2314268.262      374150.272     2314473.124      374009.647
     2314455.762      373886.383     2314540.832       373740.55
     2315768.262      373228.397     2315919.304      373184.994
     2316169.304      373231.869     2316287.089      373204.751

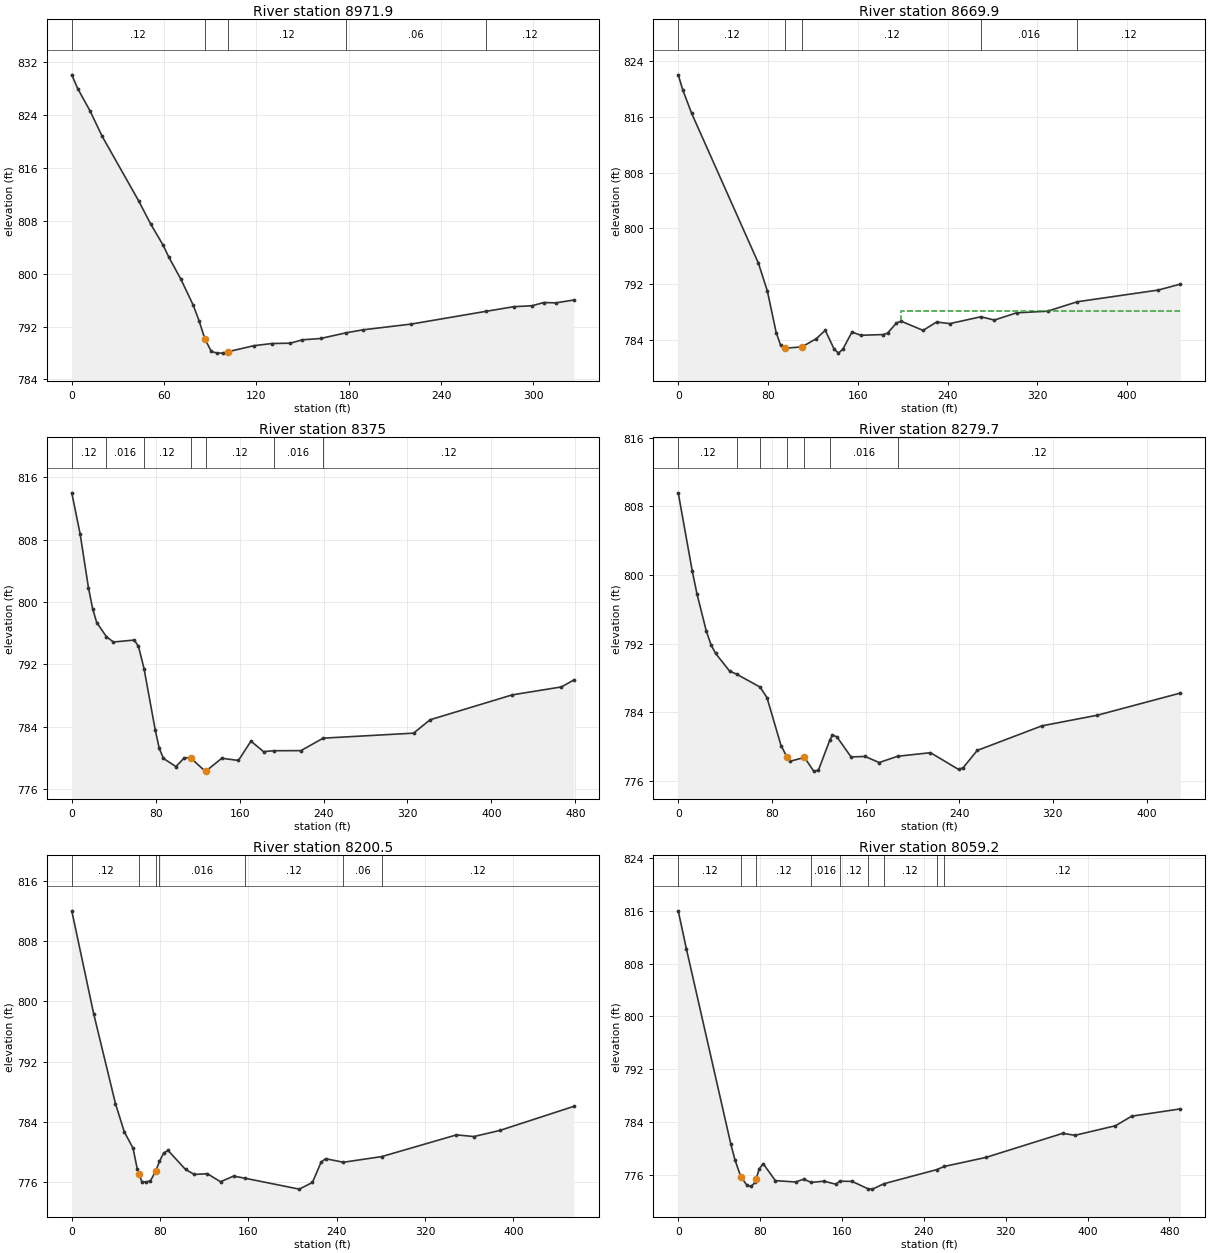
Type RM Length L Ch R = 1 ,8971.9  ,303.3,302,300.6
XS GIS Cut Line= 3
     2310922.224      378196.063     2310731.914      378109.644
     2310614.627       378107.05
#Sta/Elev= 30
       0     830     3.9  827.91    11.8  824.59    19.7  820.74    43.4     811
    51.3  807.47    59.2  804.35    63.1  802.47      71   799.1    78.9  795.24
    82.8  792.82    86.5  790.13    90.7  788.23    94.6  787.98    98.6  787.99
   101.5  788.19   118.3   789.1   130.1  789.43     142  789.48   149.9  789.99
   161.7  790.19  178.43791.0558   189.3   791.5   220.7  792.37  269.36794.2981
   287.2  794.99     299  795.13   306.8  795.62   314.6  795.57   326.3     796
#Mann= 5 ,-1 , 0
       0     .12       0    86.5    .045       0   101.5     .12       0
  178.43     .06       0  269.36     .12       0
Bank Sta=86.5,101.5
XS Rating Curve= 0 ,0
Exp/Cntr=0.3,0.1

Type RM Length L Ch R = 1 ,8669.9  ,297.6,294.9,292.1
XS GIS Cut Line= 3
     2311003.703      377902.909     2310737.128      377800.132
     2310578.683      377832.537
#Sta/Elev= 30
       0     822       4  819.86    11.9   816.5    71.4  795.02    79.4  791.03
    87.3  785.05    91.3  783.22    95.3  782.81   110.3  783.01     123  784.18
     131  785.38   138.9   782.7   142.8  782.11   146.8  782.71   154.8  785.13
   162.7  784.67   182.5  784.77   186.5  784.97   194.4  786.42   198.4   786.7
   218.2  785.37   230.2  786.57     242  786.34  269.67787.3214   281.7  786.85
   301.5  787.89   329.1  788.12   355.5789.4708   427.7  791.15   447.4     792
#Mann= 5 ,-1 , 0
       0     .12       0    95.3    .045       0   110.3     .12       0
  269.67    .016       0   355.5     .12       0
#XS Ineff= 2 , 0
                          198.13          788.12
Permanent Ineff=
       F       F
Bank Sta=95.3,110.3
XS Rating Curve= 0 ,0
Exp/Cntr=0.3,0.1

Type RM Length L Ch R = 1 ,8375    ,87.1,95.3,103.5
XS GIS Cut Line= 3
     2311129.576      377632.145     2310805.913      377550.739
      2310661.42      377560.537
#Sta/Elev= 30
       0     814       8  808.71    15.9  801.83    19.9  799.13    23.8  797.36
   33.05795.5469    39.7  794.87    59.6  795.12    63.6   794.3   68.88791.4633
    79.5  783.63    83.4  781.22    87.4  779.94    99.3  778.89   107.3  780.02
   113.2  780.02   127.1  778.31   128.2  778.35     143  779.96   158.9  779.68
   170.8  782.16   182.8  780.81  192.57780.9258   218.5  780.94  239.64782.5379
   325.8  783.18   341.6   784.9   419.9  788.09   466.8  789.11   478.6     790
#Mann= 7 ,-1 , 0
       0     .12       0   33.05    .016       0   68.88     .12       0
   113.2    .045       0   128.2     .12       0  192.57    .016       0
  239.64     .12       0
Bank Sta=113.2,128.2
XS Rating Curve= 0 ,0
Exp/Cntr=0.3,0.1

Type RM Length L Ch R = 1 ,8279.7  ,79.2,79.2,79.3
XS GIS Cut Line= 3
     2311139.952        377576.1     2310920.331      377423.722
     2310761.606      377453.338
#Sta/Elev= 30
       0  809.57      12  800.43      16  797.79    23.9  793.49    27.9  791.88
    31.9  790.85    43.9  788.78      50788.4182   69.87786.9213    75.8  785.69
    87.8   780.1    92.8  778.79    95.8  778.28   107.8  778.72   115.7  777.12
   119.7  777.22  129.32780.6915   131.7  781.34   135.6   781.1   147.6  778.78
   159.6  778.83   171.6  778.12  187.39778.8531   215.4  779.27   239.4  777.32
   243.4  777.53   255.3  779.53   310.6   782.4   357.9  783.64   428.8  786.22
#Mann= 7 ,-1 , 0
       0     .12       0      50    .016       0   69.87     .12       0
    92.8    .045       0   107.8     .12       0  129.32    .016       0
  187.39     .12       0
Bank Sta=92.8,107.8
XS Rating Curve= 0 ,0
Exp/Cntr=0.3,0.1

Type RM Length L Ch R = 1 ,8200.5  ,149.7,141.3,132.7
XS GIS Cut Line= 3
     2311158.423      377492.537     2310917.628      377325.229
     2310758.903      377354.845
#Sta/Elev= 30
       0     812    19.8  798.37    39.6  786.39    47.6  782.65    55.5   780.5
    59.4  777.67    60.9  777.07    63.4  776.06    67.4     776    71.3  776.18
    75.9  777.41    79.4 778.729    83.2  779.85    87.2   780.2     103  777.67
     111  777.01   122.8  777.11   134.7  776.04   146.6  776.79  156.75776.5112
     206  775.06   217.9  775.94   225.8  778.63   229.8   779.1  246.05778.6281
   280.7779.3785   348.4  782.26   364.1  782.04   387.7  782.85   454.7  786.05
#Mann= 7 ,-1 , 0
       0     .12       0    60.9    .045       0    75.9     .12       0
    79.4    .016       0  156.75     .12       0  246.05     .06       0
   280.7     .12       0
Bank Sta=60.9,75.9
XS Rating Curve= 0 ,0
Exp/Cntr=0.3,0.1

Type RM Length L Ch R = 1 ,8059.2  ,304.8,295.5,286.3
XS GIS Cut Line= 3
     2311221.315      377340.902     2310951.931      377277.205
      2310740.85      377311.802
#Sta/Elev= 30
       0     816     7.9  810.29    51.4  780.67    55.4  778.31    61.1  775.75
    67.2  774.42    71.2  774.26    75.1  774.87    76.1  775.38    79.1   776.9
      83  777.71    94.9  775.14   114.7  774.93   122.6  775.36  129.93774.8728
   142.4  775.05   154.2  774.59  157.69775.0524     170  775.02  185.79773.8774
   189.8  773.85  201.16774.6736  252.46776.7952  260.22777.2913   300.6  778.65
   375.8   782.3   387.7     782   427.3  783.45   443.2   784.9   490.7     786
#Mann= 9 ,-1 , 0
       0     .12       0    61.1    .045       0    76.1     .12       0
  129.93    .016       0  157.69     .12       0  185.79     .06       0
  201.16     .12       0  252.46     .06       0  260.22     .12       0
Bank Sta=61.1,76.1
XS Rating Curve= 0 ,0
Exp/Cntr=0.3,0.1

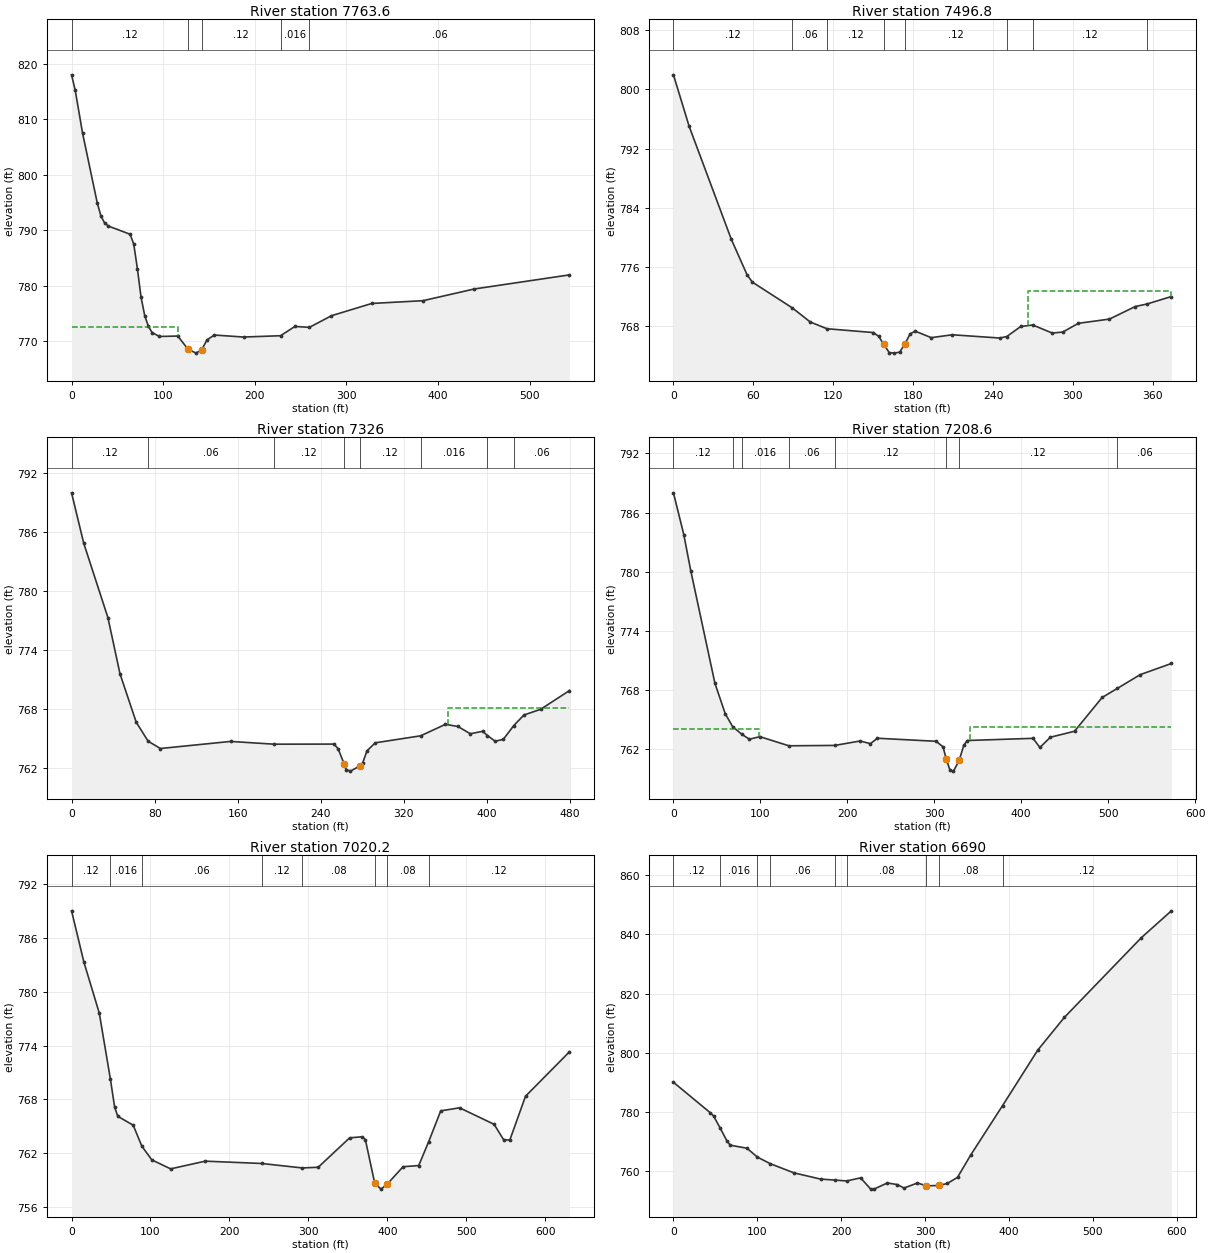
Type RM Length L Ch R = 1 ,7763.6  ,262.6,266.9,271.2
XS GIS Cut Line= 2
      2311292.57      377015.912     2310757.234      377109.689
#Sta/Elev= 30
       0     818       4  815.21      12   807.5      28  794.95      32  792.59
      36  791.33      40  790.76    63.9  789.27    67.9  787.48    71.9  783.01
    75.9  777.88    79.9  774.58    83.9  772.68    87.9  771.56    95.9  770.85
   115.9  770.93   127.1  768.57   135.9  767.85   142.1  768.49   147.9  770.24
   155.8  771.11   187.8  770.75  228.14770.9874   243.8  772.66  259.61772.4929
   283.7  774.59   327.7   776.8   383.6   777.3   439.6  779.41   543.5  781.95
#Mann= 5 ,-1 , 0
       0     .12       0   127.1    .045       0   142.1     .12       0
  228.14    .016       0  259.61     .06       0
#XS Ineff= 2 , 0
          115.79  772.57
Permanent Ineff=
       F       F
Bank Sta=127.1,142.1
XS Rating Curve= 0 ,0
Exp/Cntr=0.3,0.1

Type RM Length L Ch R = 1 ,7496.8  ,185.5,170.8,155.9
XS GIS Cut Line= 3
     2311313.369      376775.283     2311013.143       376770.53
     2310953.964      376814.387
#Sta/Elev= 30
       0  801.96    11.8  794.99    43.5  779.71    55.3  774.93    59.3  773.94
   89.33770.4559   102.7  768.56  115.28767.6461   150.1  767.13   154.1  766.62
     158  765.52     162  764.43   165.9  764.35   169.9  764.49   173.8   765.6
   177.8  766.97   181.7  767.31   193.6  766.44   209.4  766.83     245  766.39
  250.32766.5947   260.8  767.95  269.83768.1494   284.5  767.06   292.4   767.2
   304.1  768.38   327.4  768.95   346.8  770.65  355.64770.9893   373.9     772
#Mann= 8 ,-1 , 0
       0     .12       0   89.33     .06       0  115.28     .12       0
     158    .045       0   173.8     .12       0  250.32    .016       0
  269.83     .12       0  355.64     .06       0
#XS Ineff= 2 , 0
                          265.91          772.81
Permanent Ineff=
       F       F
Bank Sta=158,173.8
XS Rating Curve= 0 ,0
Exp/Cntr=0.3,0.1

Type RM Length L Ch R = 1 ,7326    ,117.2,117.3,117.7
XS GIS Cut Line= 3
     2311371.322      376508.189      2311286.62      376496.537
     2310964.469      376723.152
#Sta/Elev= 30
       0     790    11.7  784.88      35  777.31    46.6  771.61    62.2  766.69
   73.67764.7468    85.5     764   153.1  764.72  194.86764.4406   252.6  764.45
   256.6  763.99   262.6  762.39   264.5  761.86   268.5   761.7   277.6  762.23
   280.4  762.56   284.4  763.76   292.4  764.58  336.08  765.29     360  766.46
     372  766.24   383.9   765.5   395.8  765.75  400.37765.3216   407.8  764.74
   415.7  764.93  425.73766.3307   435.6  767.41   451.5  767.98   479.4  769.89
#Mann= 8 ,-1 , 0
       0     .12       0   73.67     .06       0  194.86     .12       0
   262.6    .045       0   277.6     .12       0  336.08    .016       0
  400.37     .12       0  425.73     .06       0
#XS Ineff= 2 , 0
                          362.92          768.14
Permanent Ineff=
       F       F
Bank Sta=262.6,277.6
XS Rating Curve= 0 ,0
Exp/Cntr=0.3,0.1

Type RM Length L Ch R = 1 ,7208.6  ,167.2,188.4,209.5
XS GIS Cut Line= 3
      2311382.94      376492.537     2311226.203      376406.433
     2310904.053      376633.048
#Sta/Elev= 30
       0     788    11.9  783.76    19.9  780.09    47.7  768.66    59.6  765.56
   68.16764.2483   78.67763.4815    87.4  762.98    99.4  763.24  132.76762.3124
  185.53762.3505   214.6   762.8   226.6  762.53   234.5  763.08   302.2  762.77
   310.1   762.2   313.7  760.99   318.1  759.83   322.1  759.74   328.7  760.85
     334  762.38     338  762.85   413.6  763.07   421.5  762.14   433.5  763.18
   461.3  763.79   493.1  767.22  510.69768.1465   536.9  769.54   572.7  770.67
#Mann= 8 ,-1 , 0
       0     .12       0   68.16     .06       0   78.67    .016       0
  132.76     .06       0  185.53     .12       0   313.7    .045       0
   328.7     .12       0  510.69     .06       0
#XS Ineff= 2 , 0
           97.83  764.05  340.56          764.22
Permanent Ineff=
       F       F
Bank Sta=313.7,328.7
XS Rating Curve= 0 ,0
Exp/Cntr=0.3,0.1

Type RM Length L Ch R = 1 ,7020.2  ,309.9,330.2,350.5
XS GIS Cut Line= 3
     2311402.785      376482.669     2311361.942      376398.365
     2310849.648      376236.854
#Sta/Elev= 30
       0  789.04    15.6  783.33    35.1  777.64    49.2770.2739    54.6  767.13
    58.6  766.12    78.1  765.13   89.05762.7877   101.6  761.27   125.5  760.26
   169.3  761.12  240.81760.8611  292.33760.3627   312.5  760.44   352.3  763.72
   368.2  763.84   372.2  763.53   384.1  758.65   392.1     758     400  758.57
     420   760.5   439.8  760.63  452.36763.2766   467.7  766.73   491.6  767.07
   535.3  765.23   547.3  763.52   555.2  763.47   575.1  768.36   630.8  773.32
#Mann= 8 ,-1 , 0
       0     .12       0    49.2    .016       0   89.05     .06       0
  240.81     .12       0  292.33     .08       0   384.1    .045       0
     400     .08       0  452.36     .12       0
Bank Sta=384.1,400
XS Rating Curve= 0 ,0
Exp/Cntr=0.3,0.1

Type RM Length L Ch R = 1 ,6690    ,284.3,288.3,292.4
XS GIS Cut Line= 2
     2311440.449      376480.872     2311216.114      375931.403
#Sta/Elev= 30
       0  789.99    43.8  779.71    47.8   778.6   55.44774.6225    63.7  770.18
    67.7   768.7    87.6  767.68   99.95 764.697  115.25  762.47   143.4  759.36
   175.3  757.24  192.94756.8904  206.49756.5993   223.1  757.66     235  753.87
     239  753.84   254.9  755.92   266.9  755.38   274.8   754.2   290.8  755.92
   301.4  754.96   316.4  755.07   326.6  755.77   338.6  757.83   354.5  765.46
  392.28782.0893   434.2  800.86     466  811.96   557.6  838.88   593.5     848
#Mann= 9 ,-1 , 0
       0     .12       0   55.44    .016       0   99.95     .12       0
  115.25     .06       0  192.94     .12       0  206.49     .08       0
   301.4    .045       0   316.4     .08       0  392.28     .12       0
Bank Sta=301.4,316.4
XS Rating Curve= 0 ,0
Exp/Cntr=0.3,0.1

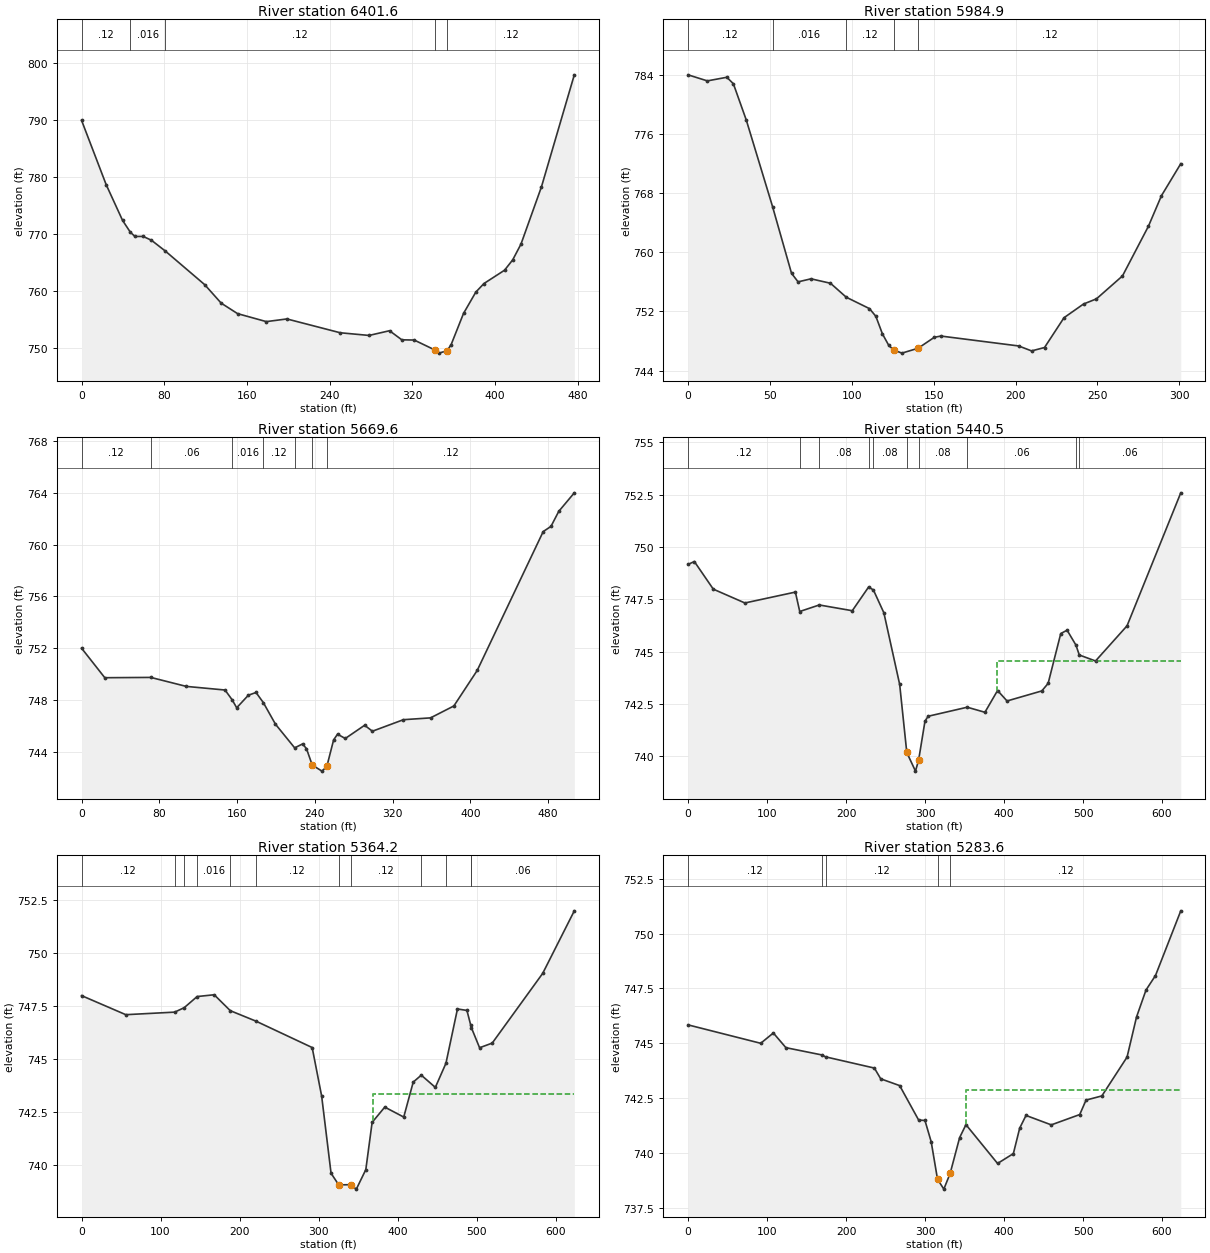
Type RM Length L Ch R = 1 ,6401.6  ,419.8,416.7,413.6
XS GIS Cut Line= 2
     2311644.114      376425.875     2311556.114       375957.23
#Sta/Elev= 30
       0     790    23.8   778.7    39.7   772.4   47.21770.3301    51.7  769.58
    59.6  769.59    67.6  768.92   81.05767.0182   119.2   761.1   135.1  757.86
     151  756.01   178.8  754.61   198.7  755.08   250.3  752.65   278.2  752.18
     298  753.01   309.9  751.41   321.9  751.37   341.7  749.64   345.7  749.07
   353.6  749.48   357.6  750.56   369.6  756.05   381.5   759.8   389.4  761.31
   409.3  763.65   417.2  765.47   425.2  768.24     445   778.3   476.8     798
#Mann= 5 ,-1 , 0
       0     .12       0   47.21    .016       0   81.05     .12       0
   341.7    .045       0   353.6     .12       0
Bank Sta=341.7,353.6
XS Rating Curve= 0 ,0
Exp/Cntr=0.3,0.1

Type RM Length L Ch R = 1 ,5984.9  ,317.2,315.3,313.1
XS GIS Cut Line= 3
     2311980.114      376254.636     2311992.061       376196.59
     2311909.151      375969.574
#Sta/Elev= 30
       0     784    11.8  783.18    23.7  783.67    27.7  782.79    35.6  777.87
    51.6766.1902    63.2  757.16    67.2     756    75.1  756.41      87  755.81
   96.63753.9205   110.8  752.38   114.7  751.34   118.7  748.97   122.6   747.4
   125.5   746.8   130.6  746.36   140.5  747.02   150.4   748.5   154.4  748.67
   201.9  747.33   209.8  746.66   217.7  747.12   229.6  751.15   241.5     753
   249.4   753.7   265.3   756.8   281.1   763.5   289.1  767.65   300.9  771.98
#Mann= 5 ,-1 , 0
       0     .12       0    51.6    .016       0   96.63     .12       0
   125.5    .045       0   140.5     .12       0
Bank Sta=125.5,140.5
XS Rating Curve= 0 ,0
Exp/Cntr=0.3,0.1

Type RM Length L Ch R = 1 ,5669.6  ,227.1,229.1,230.8
XS GIS Cut Line= 3
     2312306.188      376192.313       2312145.3       375840.37
     2312034.691       375793.96
#Sta/Elev= 30
       0     752    23.9  749.72   71.24749.7428   107.7  749.05   147.6  748.77
  154.81748.0266   159.6   747.4   171.6  748.37   179.5  748.58  187.03747.7946
   199.5  746.13  219.24744.3052   227.4  744.61   231.4  744.24   237.3  742.98
   247.3  742.51   252.3  742.87   259.3  744.92   263.3  745.36   271.3  745.03
   291.2  746.05   299.2  745.59   331.1  746.48     359  746.62     383  747.54
     407  750.28   474.9     761   482.9   761.4   490.9  762.56   506.9  763.99
#Mann= 7 ,-1 , 0
       0     .12       0   71.24     .06       0  154.81    .016       0
  187.03     .12       0  219.24     .08       0   237.3    .045       0
   252.3     .12       0
Bank Sta=237.3,252.3
XS Rating Curve= 0 ,0
Exp/Cntr=0.3,0.1

Type RM Length L Ch R = 1 ,5440.5  ,65.9,76.4,78.7
XS GIS Cut Line= 2
     2312492.227      376115.912     2312279.589      375529.575
#Sta/Elev= 30
       0  749.16       8   749.3      32  747.98      72  747.32   135.9  747.84
   141.4746.9125  166.14747.2248   207.9  746.95  228.57748.0815  234.65747.9418
   247.9  746.85   267.9  743.43   276.9  740.18   287.9  739.29   291.9  739.82
   299.9  741.67   303.9  741.91  353.43742.3422   375.8   742.1   391.8  743.14
   403.8  742.64   447.8  743.12   455.8  743.48   471.8  745.86   479.8  746.02
  491.02745.3077  495.21744.8364   515.8  744.55   555.7  746.23   623.7  752.58
#Mann= 10 ,-1 , 0
       0     .12       0   141.4    .016       0  166.14     .08       0
  228.57     .12       0  234.65     .08       0   276.9    .045       0
   291.9     .08       0  353.43     .06       0  491.02     .08       0
  495.21     .06       0
#XS Ineff= 2 , 0
                          390.82          744.54
Permanent Ineff=
       F       F
Bank Sta=276.9,291.9
XS Rating Curve= 0 ,0
Exp/Cntr=0.3,0.1

Type RM Length L Ch R = 1 ,5364.2  ,89.5,80.5,79.6
XS GIS Cut Line= 2
     2312546.451      376098.874     2312333.812      375512.537
#Sta/Elev= 30
       0     748      56   747.1  117.87747.2205  129.95747.4312  146.29747.9557
   167.9  748.04  188.29747.2883   220.7 746.796   291.9  745.55   303.9  743.26
   315.8  739.62   325.5  739.07   340.5  739.08   347.8  738.87   359.8  739.79
   367.8  742.02   383.8  742.74   407.8  742.27   419.8  743.92  430.01744.2468
   447.8  743.67  461.23744.8088   475.8  747.37   487.8   747.3  492.44746.6272
  493.37746.4923   503.8  745.54   519.8  745.76   583.7  749.05   623.7     752
#Mann= 12 ,-1 , 0
       0     .12       0  117.87     .08       0  129.95     .12       0
  146.29    .016       0  188.29     .08       0   220.7     .12       0
   325.5    .045       0   340.5     .12       0  430.01     .06       0
  461.23     .08       0  492.44    .016       0  493.37     .06       0
#XS Ineff= 2 , 0
                          369.14          743.34
Permanent Ineff=
       F       F
Bank Sta=325.5,340.5
XS Rating Curve= 0 ,0
Exp/Cntr=0.3,0.1

Type RM Length L Ch R = 1 ,5283.6  ,59.8,60,59.8
XS GIS Cut Line= 2
     2312617.631      376062.415     2312404.993      375476.079
#Sta/Elev= 30
       0  745.84      92     745     108  745.47   123.9   744.8  169.12744.4708
  174.21744.3807   235.9  743.87   243.9  743.38   267.9  743.07   291.9   741.5
   299.9  741.48   307.8  740.51   315.8   738.8   323.8  738.35   331.8  739.07
   343.8   740.7   351.8  741.29   391.8  739.52   411.8  739.97   419.8  741.13
   427.8  741.71   459.8  741.28   495.8  741.75   503.8  742.41   523.8   742.6
   555.7  744.37   567.7   746.2   579.7  747.43   591.7  748.09   623.7  751.04
#Mann= 5 ,-1 , 0
       0     .12       0  169.12     .08       0  174.21     .12       0
   315.8    .045       0   331.8     .12       0
#XS Ineff= 2 , 0
                          351.81          742.85
Permanent Ineff=
       F       F
Bank Sta=315.8,331.8
XS Rating Curve= 0 ,0
Exp/Cntr=0.3,0.1

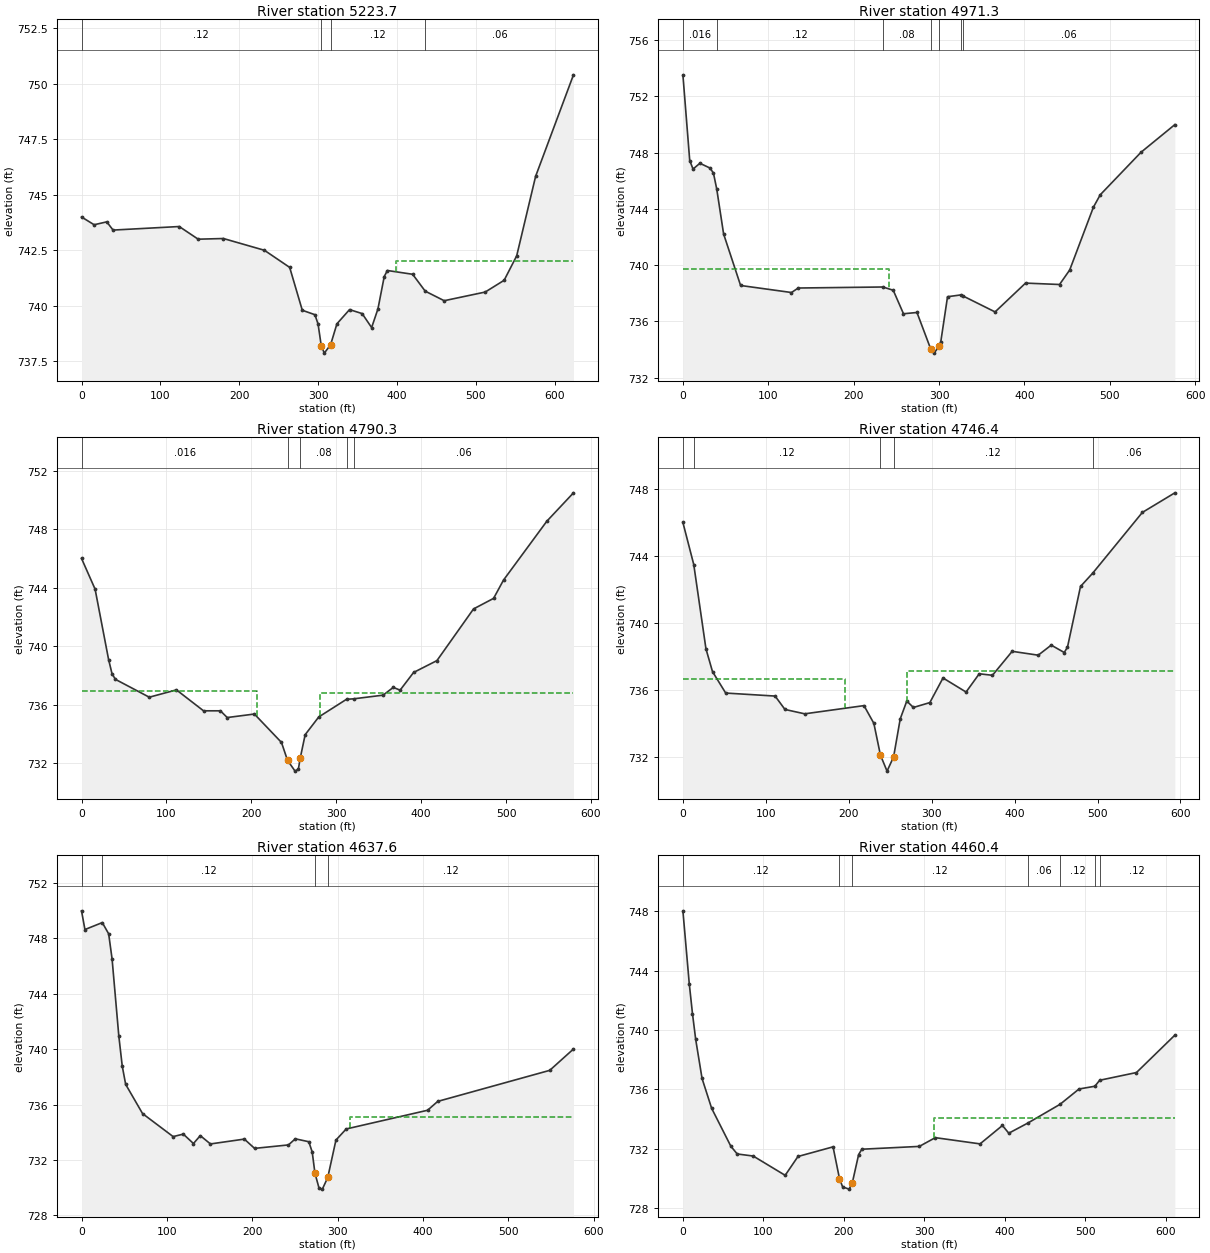
Type RM Length L Ch R = 1 ,5223.7  ,259.6,252.4,244.9
XS GIS Cut Line= 2
     2312670.434       376034.34     2312457.795      375448.004
#Sta/Elev= 30
       0     744      16  743.65      32  743.78      40  743.41   123.9  743.57
   147.9     743   179.9  743.03   231.9   742.5   263.9  741.73   279.9   739.8
   295.9   739.6   299.9  739.18   303.9  738.21   307.8  737.87   315.8  738.25
   323.8  739.19   339.8  739.83   355.8  739.65   367.8  739.02   375.8  739.86
   383.8  741.32   387.8  741.59   419.8  741.42  435.72740.6609   459.8  740.23
   511.8  740.62   535.8  741.15   551.7  742.25   575.7  745.83   623.7   750.4
#Mann= 4 ,-1 , 0
       0     .12       0   303.9    .045       0   315.8     .12       0
  435.72     .06       0
#XS Ineff= 2 , 0
                          398.76             742
Permanent Ineff=
       F       F
Bank Sta=303.9,315.8
XS Rating Curve= 0 ,0
Exp/Cntr=0.3,0.1

Type RM Length L Ch R = 1 ,4971.3  ,173.7,181.1,188.1
XS GIS Cut Line= 2
     2312920.775      375814.707     2312536.646      375385.069
#Sta/Elev= 30
       0  753.54       8  747.44    11.9  746.84    19.9  747.25    31.8  746.91
    35.8  746.55   39.67745.4083    47.7  742.22    67.6  738.56   127.2  738.06
   135.1  738.38  234.34738.4528   246.4  738.22   258.4  736.55   274.2  736.64
   290.2  734.06   294.1  733.75   300.4  734.24   302.1  734.56     310  737.76
  326.26737.8947  328.19737.8126   365.7  736.68   401.4  738.73   441.2  738.63
   453.1  739.66   480.9  744.13   488.9  745.01   536.6  748.03   576.3     750
#Mann= 7 ,-1 , 0
       0    .016       0   39.67     .12       0  234.34     .08       0
   290.2    .045       0   300.4     .08       0  326.26     .12       0
  328.19     .06       0
#XS Ineff= 2 , 0
          240.87  739.71
Permanent Ineff=
       F       F
Bank Sta=290.2,300.4
XS Rating Curve= 0 ,0
Exp/Cntr=0.3,0.1

Type RM Length L Ch R = 1 ,4790.3  ,44.1,43.9,43.9
XS GIS Cut Line= 3
     2312955.991      375704.661     2312792.114      375353.892
     2312632.599      375246.525
#Sta/Elev= 30
       0     746      16   743.9    31.9  739.09    35.9  738.13    39.9  737.74
    79.8  736.52   111.8  737.02   143.7  735.59   163.6  735.59   171.6  735.13
   203.6  735.37   235.5  733.43   242.6  732.21   251.5  731.47   255.4  731.61
   257.6  732.36   263.4  733.96   279.4  735.17  312.13736.3779  320.41736.4078
   355.2  736.66   367.2  737.19   375.2     737   391.1  738.21   418.6  739.02
   461.7  742.55   485.3  743.27     497  744.52     548  748.54   579.4  750.48
#Mann= 5 ,-1 , 0
       0    .016       0   242.6    .045       0   257.6     .08       0
  312.13     .12       0  320.41     .06       0
#XS Ineff= 2 , 0
          206.19  736.93  281.11          736.84
Permanent Ineff=
       F       F
Bank Sta=242.6,257.6
XS Rating Curve= 0 ,0
Exp/Cntr=0.3,0.1

Type RM Length L Ch R = 1 ,4746.4  ,106.3,108.8,111.4
XS GIS Cut Line= 3
     2312987.881      375672.537     2312816.696      375309.844
      2312657.18      375202.478
#Sta/Elev= 30
       0     746    13.1 743.489    27.8  738.46    35.7   737.1    51.6  735.82
   111.2  735.64   123.1  734.84   146.9  734.58   218.4  735.07   230.3  734.01
   238.2  732.12   246.2  731.16   254.1  732.01   262.1  734.28     270  735.34
     278  734.96   297.8  735.25   313.7  736.72   341.5  735.88   357.4  736.97
   373.3  736.88   397.1  738.31   428.5  738.08   444.2  738.68   459.9  738.24
   463.8  738.56   479.5  742.18  494.37742.9845   554.1   746.6   593.3  747.77
#Mann= 5 ,-1 , 0
       0    .016       0    13.1     .12       0   238.2    .045       0
   254.1     .12       0  494.37     .06       0
#XS Ineff= 2 , 0
          195.05  736.66  270.59          737.11
Permanent Ineff=
       F       F
Bank Sta=238.2,254.1
XS Rating Curve= 0 ,0
Exp/Cntr=0.3,0.1

Type RM Length L Ch R = 1 ,4637.6  ,170.5,177.1,183.9
XS GIS Cut Line= 2
     2313060.881      375657.304     2312881.361      375109.784
#Sta/Elev= 30
       0  749.98       4  748.63   24.33749.1315    31.8  748.32    35.8  746.51
    43.7  740.94    47.7  738.78    51.7  737.46    71.5  735.35   107.3  733.69
   119.2  733.87   131.1  733.19   139.1  733.76     151  733.16   190.7  733.51
   202.7  732.84   242.4  733.09   250.4  733.53   266.2  733.32   270.2  732.58
   273.4  731.05   278.2  729.97   282.1   729.9   288.4  730.74     298  733.44
     310  734.24   405.3  735.59   417.2  736.23   548.4  738.47   576.2  740.01
#Mann= 4 ,-1 , 0
       0    .016       0   24.33     .12       0   273.4    .045       0
   288.4     .12       0
#XS Ineff= 2 , 0
                          313.93          735.09
Permanent Ineff=
       F       F
Bank Sta=273.4,288.4
XS Rating Curve= 0 ,0
Exp/Cntr=0.3,0.1

Type RM Length L Ch R = 1 ,4460.4  ,189.5,190.5,191.4
XS GIS Cut Line= 3
     2313152.648      375589.071     2313143.445      375160.321
     2312997.461      375050.792
#Sta/Elev= 30
       0  748.03     7.9  743.12    11.9   741.1    15.9  739.36    23.8  736.73
    35.7  734.72    59.6  732.16    67.5  731.64    87.4   731.5   127.1   730.2
     143  731.47   186.6  732.12   194.6  729.98   198.5  729.42   206.5  729.27
   210.4  729.66   218.4   731.6   222.4  731.96   293.8  732.15   313.7  732.74
   369.3  732.32   397.1  733.56     405  733.04   428.7733.7244  468.74734.9884
   492.3  736.02  511.96 736.205  517.96736.6084   563.7  737.13   611.4  739.65
#Mann= 7 ,-1 , 0
       0     .12       0   194.6    .045       0   210.4     .12       0
   428.7     .06       0  468.74     .12       0  511.96     .06       0
  517.96     .12       0
#XS Ineff= 2 , 0
                          312.07          734.08
Permanent Ineff=
       F       F
Bank Sta=194.6,210.4
XS Rating Curve= 0 ,0
Exp/Cntr=0.3,0.1

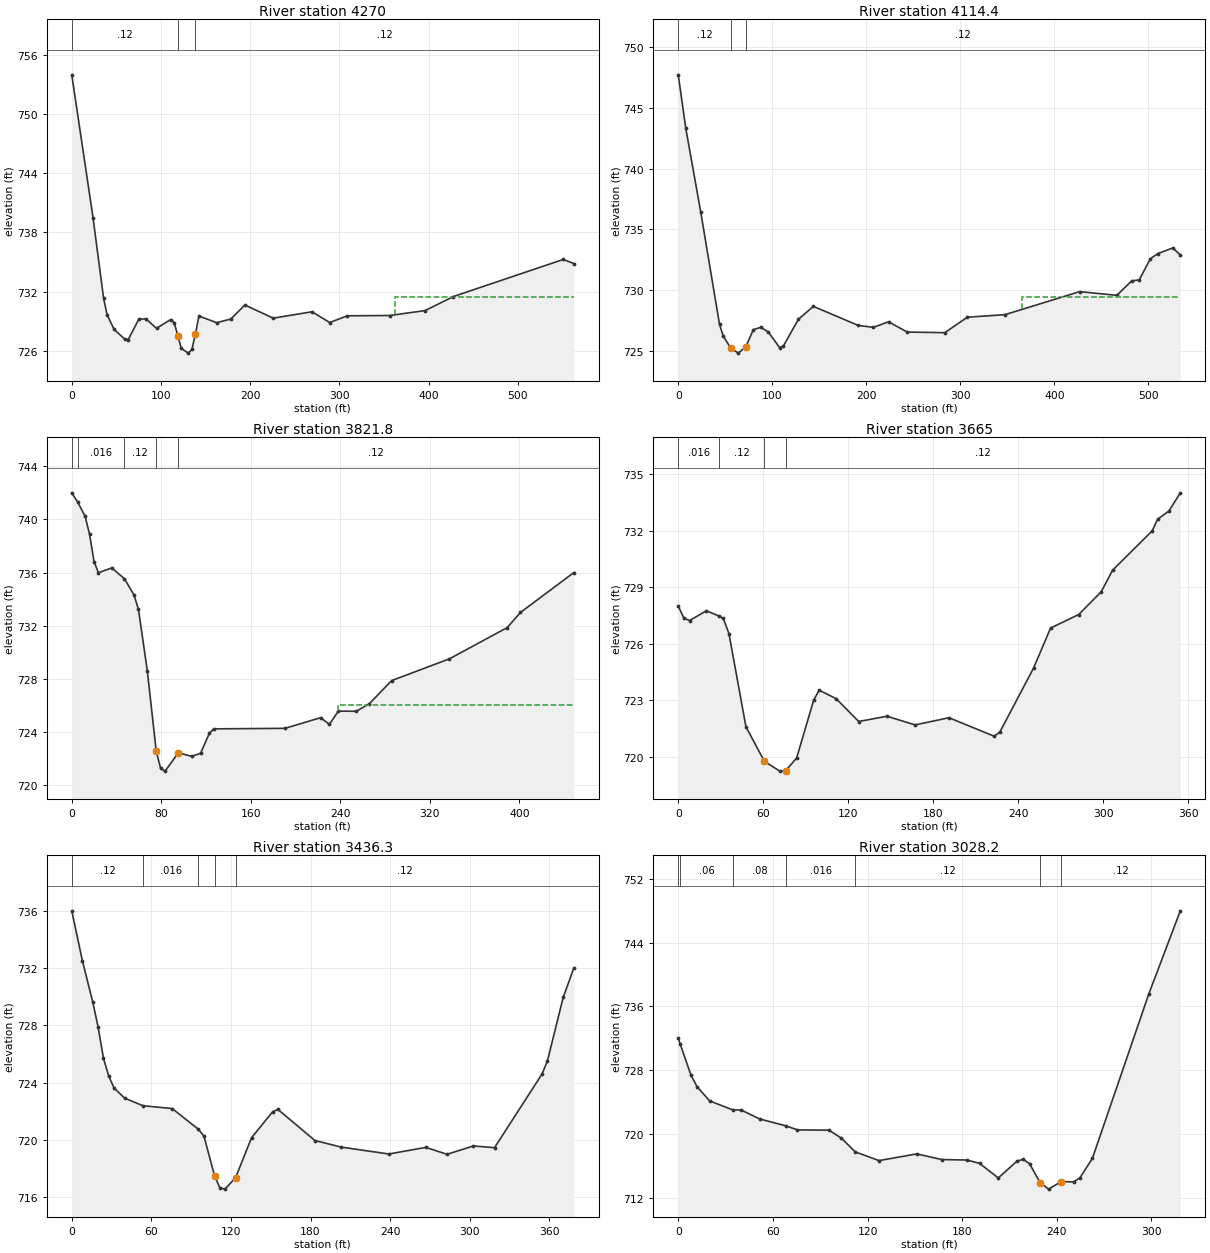
Type RM Length L Ch R = 1 ,4270    ,156,155.5,155.4
XS GIS Cut Line= 3
     2313333.868      375526.291     2313340.504      375146.282
      2313194.52      375036.752
#Sta/Elev= 30
       0  754.01    23.8  739.52    35.6  731.36    39.6  729.64    47.5  728.15
    59.4  727.17    63.3  727.13    75.2  729.21    83.1  729.22      95  728.27
   110.8  729.16   114.8  728.83   118.8  727.54   122.7  726.23   130.6  725.75
   134.6  726.13   138.6   727.7   142.5  729.52   162.3  728.84   178.2  729.21
     194  730.64   225.7   729.3   269.2  729.95     289  728.86   308.8  729.54
   356.3  729.57   395.9  730.07   427.7   731.5   550.7  735.26   562.6  734.85
#Mann= 3 ,-1 , 0
       0     .12       0   118.8    .045       0   138.6     .12       0
#XS Ineff= 2 , 0
                           361.9          731.45
Permanent Ineff=
       F       F
Bank Sta=118.8,138.6
XS Rating Curve= 0 ,0
Exp/Cntr=0.3,0.1

Type RM Length L Ch R = 1 ,4114.4  ,310.3,292.6,274.7
XS GIS Cut Line= 3
        2313490.      375442.237     2313491.752      375090.877
     2313345.768      374981.347
#Sta/Elev= 30
       0   747.7       8  743.32      24   736.4    43.9   727.2    47.9  726.23
    55.9  725.25    63.9  724.84    71.9  725.37    79.9  726.77    87.8  726.96
    95.8  726.57   107.8   725.3   111.8  725.42   127.8  727.62   143.7  728.68
   191.6  727.11   207.6  726.96   223.6  727.41   243.6  726.57   283.5  726.52
   307.4  727.79   347.4     728   426.8  729.89   466.4  729.59   482.3  730.78
   490.2  730.85   502.1   732.6   510.1  733.02   525.9  733.48   533.9   732.9
#Mann= 3 ,-1 , 0
       0     .12       0    55.9    .045       0    71.9     .12       0
#XS Ineff= 2 , 0
                          365.94          729.43
Permanent Ineff=
       F       F
Bank Sta=55.9,71.9
XS Rating Curve= 0 ,0
Exp/Cntr=0.3,0.1

Type RM Length L Ch R = 1 ,3821.8  ,153.6,156.8,159.8
XS GIS Cut Line= 2
     2313741.543      375239.108      2313429.54      374916.537
#Sta/Elev= 30
       0     742    5.26741.3049    11.9  740.24    15.9  738.89    19.9  736.83
    23.8  735.99    35.7  736.35   47.13735.5327    55.6  734.32    59.6  733.23
    67.5  728.63    75.5  722.56    79.4  721.27    83.4  721.06    95.3  722.44
   107.2  722.17   115.2  722.41   123.1  723.93   127.1  724.24   190.6  724.28
   222.4  725.08   230.3  724.58   238.3  725.58   254.2  725.56   266.1  726.14
   285.9  727.87   337.6  729.51   389.2  731.86   401.1     733   448.8     736
#Mann= 5 ,-1 , 0
       0     .12       0    5.26    .016       0   47.13     .12       0
    75.5    .045       0    95.3     .12       0
#XS Ineff= 2 , 0
                          238.39          726.04
Permanent Ineff=
       F       F
Bank Sta=75.5,95.3
XS Rating Curve= 0 ,0
Exp/Cntr=0.3,0.1

Type RM Length L Ch R = 1 ,3665    ,232,228.7,225.3
XS GIS Cut Line= 2
     2313840.114      375130.766     2313631.188      374844.537
#Sta/Elev= 30
       0     728       4  727.36       8  727.23    19.9  727.75   28.98 727.463
    31.8  727.34    35.8  726.54    47.8   721.6    60.8  719.77    71.7  719.25
    75.8  719.27    83.6  719.95    95.6  723.01    99.5  723.54   111.5  723.09
   127.4  721.88   147.3  722.16   167.2   721.7   191.1  722.08     223   721.1
     227  721.32   250.8  724.71   262.8  726.83   282.7  727.55   298.6  728.76
   306.6   729.9   334.5  731.98   338.4   732.6   346.4  733.04   354.4     734
#Mann= 4 ,-1 , 0
       0    .016       0   28.98     .12       0    60.8    .045       0
    75.8     .12       0
Bank Sta=60.8,75.8
XS Rating Curve= 0 ,0
Exp/Cntr=0.3,0.1

Type RM Length L Ch R = 1 ,3436.3  ,415.2,408.1,401.1
XS GIS Cut Line= 2
     2314073.965      375038.388     2313808.114      374768.971
#Sta/Elev= 30
       0  735.99       8  732.51    15.9   729.6    19.9  727.87    23.9   725.7
    27.9  724.45    31.9  723.63    39.8  722.93   53.71722.3961    75.7   722.2
   95.31720.7654    99.6  720.29   107.6  717.53   111.6  716.68   115.5  716.58
   123.5  717.38   135.5  720.16   151.4  721.97   155.4  722.14   183.3  719.97
   203.2  719.51     239  719.03   266.9  719.49   282.9  719.01   302.8  719.59
   318.7  719.47   354.6  724.62   358.6  725.53   370.5  729.96   378.5     732
#Mann= 5 ,-1 , 0
       0     .12       0   53.71    .016       0   95.31     .12       0
   107.6    .045       0   123.5     .12       0
Bank Sta=107.6,123.5
XS Rating Curve= 0 ,0
Exp/Cntr=0.3,0.1

Type RM Length L Ch R = 1 ,3028.2  ,218.4,215.5,212.6
XS GIS Cut Line= 2
     2314225.048      374773.471     2313942.479      374626.901
#Sta/Elev= 30
       0  732.01     1.3 731.256       8  727.42    11.9  725.95    19.9  724.16
   34.85723.0056    39.8  723.02    51.7  721.89   68.39 721.019    75.6  720.52
    95.5  720.49   103.4  719.49  112.24717.7592   127.3  716.67   151.2  717.51
   167.1   716.8     183  716.74     191  716.33   202.9  714.49   214.9  716.63
   218.8  716.81   222.8  716.26  229.36  713.92   234.8  713.09   242.7  714.03
   250.7     714   254.7  714.52   262.6  716.97   298.4  737.62   318.3     748
#Mann= 7 ,-1 , 0
       0     .12       0     1.3     .06       0   34.85     .08       0
   68.39    .016       0  112.24     .12       0  229.36    .045       0
   242.7     .12       0
Bank Sta=229.36,242.7
XS Rating Curve= 0 ,0
Exp/Cntr=0.3,0.1