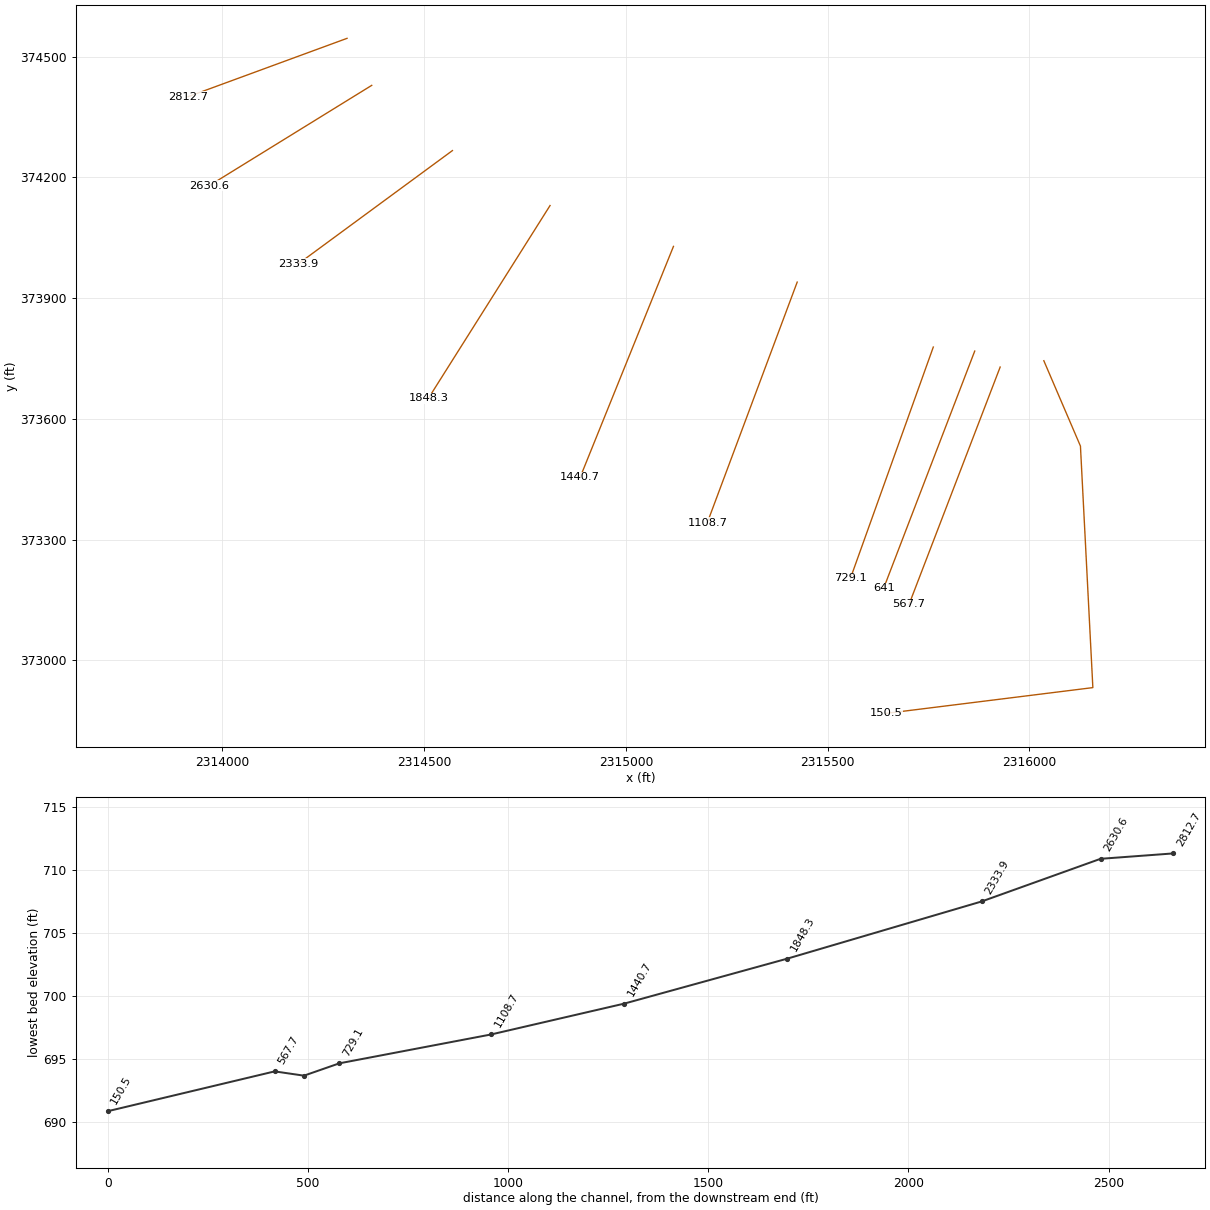
HEC-RAS study ROCKGAPRUN.prj: ROCKGAPRUN

--- ROCKGAPRUN.g01 (geometry) --- (continued)

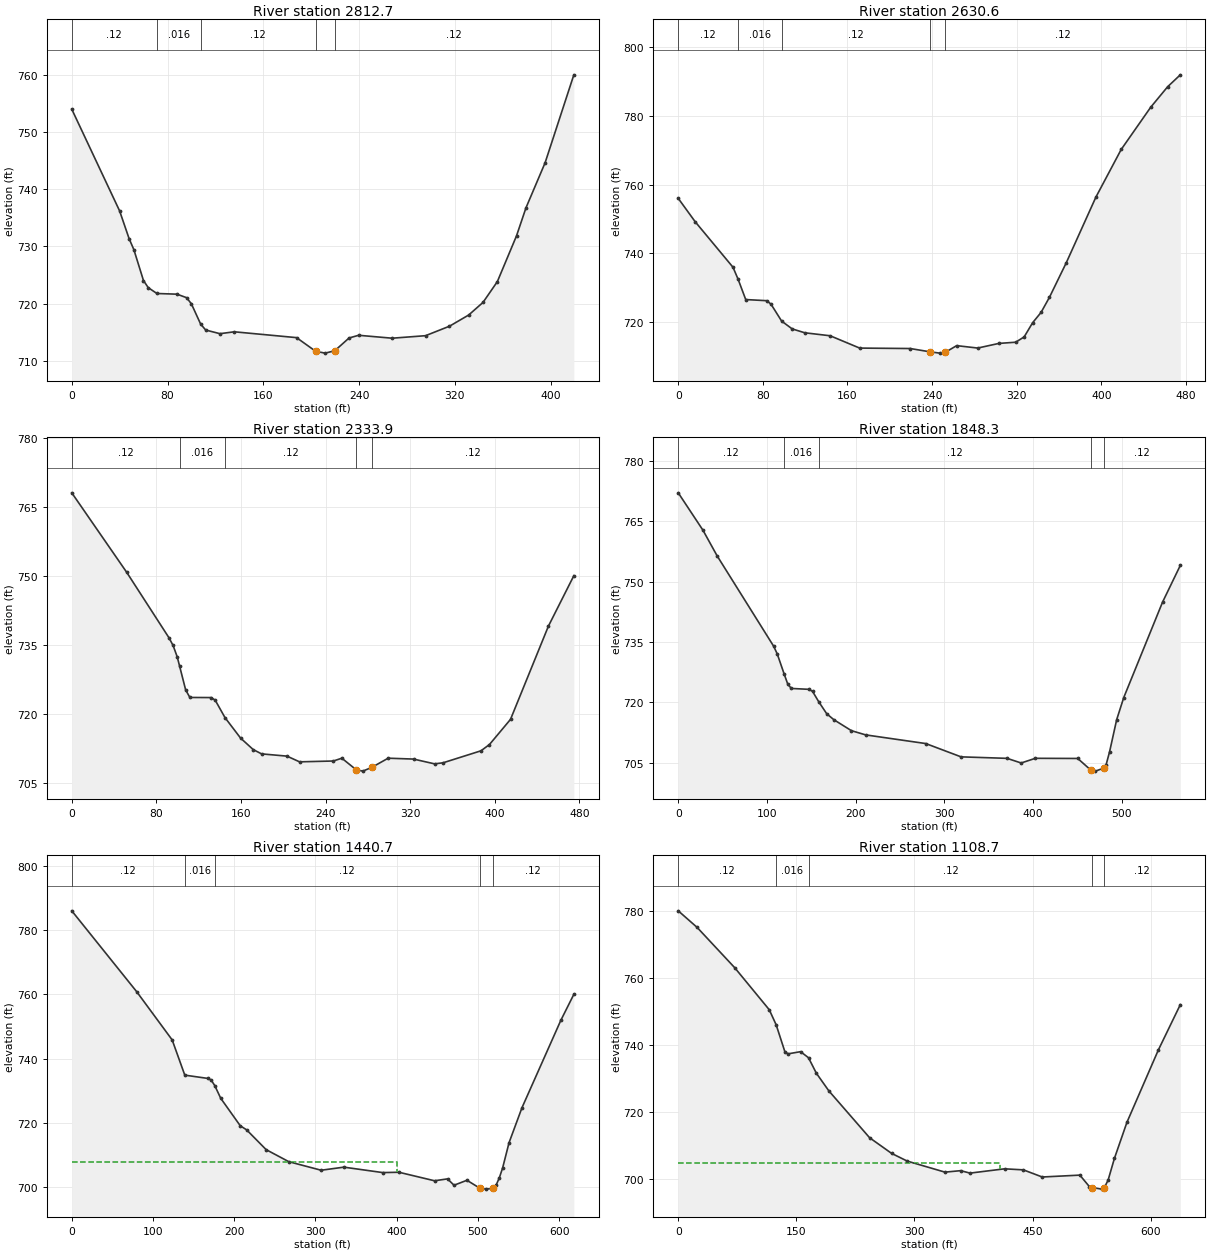
Type RM Length L Ch R = 1 ,2812.7  ,177.4,182.1,186.7
XS GIS Cut Line= 2
     2314308.933      374545.356     2313915.231      374400.537
#Sta/Elev= 30
       0  753.99      40  736.19    47.9  731.35    51.9  729.42    59.9  724.03
    63.9  722.78   71.14721.7588    87.9  721.64    95.9  721.03    99.9  719.97
   107.7 716.401   111.9  715.37   123.8  714.73   135.8  715.06   187.8  714.04
   203.8  711.65   211.7  711.33   219.7  711.74   231.7  713.98   239.7  714.45
   267.7  713.94   295.6  714.38   315.6  716.04   331.6  717.99   343.6   720.2
   355.6  723.84   371.6  731.84   379.5  736.74   395.5  744.63   419.5     760
#Mann= 5 ,-1 , 0
       0     .12       0   71.14    .016       0   107.7     .12       0
   203.8    .045       0   219.7     .12       0
Bank Sta=203.8,219.7
XS Rating Curve= 0 ,0
Exp/Cntr=0.3,0.1

Type RM Length L Ch R = 1 ,2630.6  ,293,296.7,299.7
XS GIS Cut Line= 2
     2314370.087      374428.537     2313966.491      374178.914
#Sta/Elev= 30
       0     756      16   749.2    51.8  735.91   56.67732.3657    63.8  726.51
    83.7  726.18    87.7  725.16   97.76720.2263   107.7  717.96   119.6  716.83
   143.6  715.96   171.5  712.37   219.3  712.24   237.6   711.3   247.2   710.9
   252.6  711.17   263.2  713.08   283.1  712.38   303.1  713.73     319  714.08
     327  715.63     335  719.76     343  722.78   350.9  727.17   366.9   737.3
   394.8  756.36   418.7  770.24   446.6  782.55   462.6  788.52   474.6     792
#Mann= 5 ,-1 , 0
       0     .12       0   56.67    .016       0   97.76     .12       0
   237.6    .045       0   252.6     .12       0
Bank Sta=237.6,252.6
XS Rating Curve= 0 ,0
Exp/Cntr=0.3,0.1

Type RM Length L Ch R = 1 ,2333.9  ,478.3,485.6,491.6
XS GIS Cut Line= 2
     2314570.074      374266.497      2314187.77      373984.959
#Sta/Elev= 30
       0     768    51.9  750.74    91.8  736.54    95.8  734.83    99.7  732.36
  102.05730.2685   107.7  725.16   111.7  723.52   131.7   723.5   135.6  722.95
  144.87719.1511   159.6   714.7   171.6  712.19   179.5  711.26   203.5  710.77
   215.4  709.53   247.4  709.71   255.4  710.32     269   707.8   275.3  707.51
     284  708.36   299.2  710.32   323.2  710.13   343.1  709.09   351.1  709.32
     387  711.93     395  713.29   414.9  718.76   450.8  739.05   474.8  749.99
#Mann= 5 ,-1 , 0
       0     .12       0  102.05    .016       0  144.87     .12       0
     269    .045       0     284     .12       0
Bank Sta=269,284
XS Rating Curve= 0 ,0
Exp/Cntr=0.3,0.1

Type RM Length L Ch R = 1 ,1848.3  ,403.6,407.6,411.6
XS GIS Cut Line= 2
     2314812.114      374130.041     2314510.411      373650.834
#Sta/Elev= 30
       0     772    27.9  762.72    43.9  756.35   107.7  733.92   111.7  732.02
  119.62726.9576   123.6  724.51   127.6  723.47   147.6  723.25   151.5  722.74
  158.41720.1896   167.5  717.19   175.5  715.72   195.4  712.99   211.4  711.95
   279.2   709.8     319   706.5   370.9  706.13   386.8  704.98   402.8  706.14
   450.6   706.1   465.2  703.25   470.6  702.96   480.2  703.74   482.5  704.45
   486.5  707.74   494.5  715.71   502.5  721.21   546.3   744.9   566.3     754
#Mann= 5 ,-1 , 0
       0     .12       0  119.62    .016       0  158.41     .12       0
   465.2    .045       0   480.2     .12       0
Bank Sta=465.2,480.2
XS Rating Curve= 0 ,0
Exp/Cntr=0.3,0.1

Type RM Length L Ch R = 1 ,1440.7  ,331.4,332,332.6
XS GIS Cut Line= 2
     2315118.041      374028.537     2314886.878      373455.301
#Sta/Elev= 30
       0     786    79.8  760.87   123.6  745.82  139.15734.8588   167.5  733.84
   171.5  733.36  176.03731.6115   183.4  727.65   207.4  719.11   215.3  717.82
   239.3  711.67   267.2  707.92     307  705.26     335  706.22   382.8  704.53
   402.8  704.63   446.6  701.98   462.6  702.57   470.6  700.59   486.5  702.14
   502.4  699.66   510.4  699.38   518.4  699.62   522.4  700.61   526.4  702.93
   530.4  705.94   538.3  713.81   554.3  724.75   602.1  751.93   618.1  760.01
#Mann= 5 ,-1 , 0
       0     .12       0  139.15    .016       0  176.03     .12       0
   502.4    .045       0   518.4     .12       0
#XS Ineff= 2 , 0
          400.93  707.97
Permanent Ineff=
       F       F
Bank Sta=502.4,518.4
XS Rating Curve= 0 ,0
Exp/Cntr=0.3,0.1

Type RM Length L Ch R = 1 ,1108.7  ,379.3,379.6,379.9
XS GIS Cut Line= 2
     2315424.753      373939.898     2315201.987       373342.41
#Sta/Elev= 30
       0     780    23.9  775.07    71.7  763.03   115.6  750.48  124.36745.9898
   135.5  737.91   139.5  737.31   155.4  737.96  165.47736.1479   175.4  731.54
   191.3  726.26   243.1  712.26     271   707.6   290.9  705.29   338.8     702
   358.7  702.44   370.6  701.71   414.5  702.99   438.4  702.68   462.3  700.55
   510.1  701.11   522.1  697.71   526.1   697.4     538  696.93   541.1  697.33
     546  699.62     554   706.1   569.9  716.87   609.8  738.46   637.7     752
#Mann= 5 ,-1 , 0
       0     .12       0  124.36    .016       0  165.47     .12       0
   526.1    .045       0   541.1     .12       0
#XS Ineff= 2 , 0
          408.15  704.66
Permanent Ineff=
       F       F
Bank Sta=526.1,541.1
XS Rating Curve= 0 ,0
Exp/Cntr=0.3,0.1

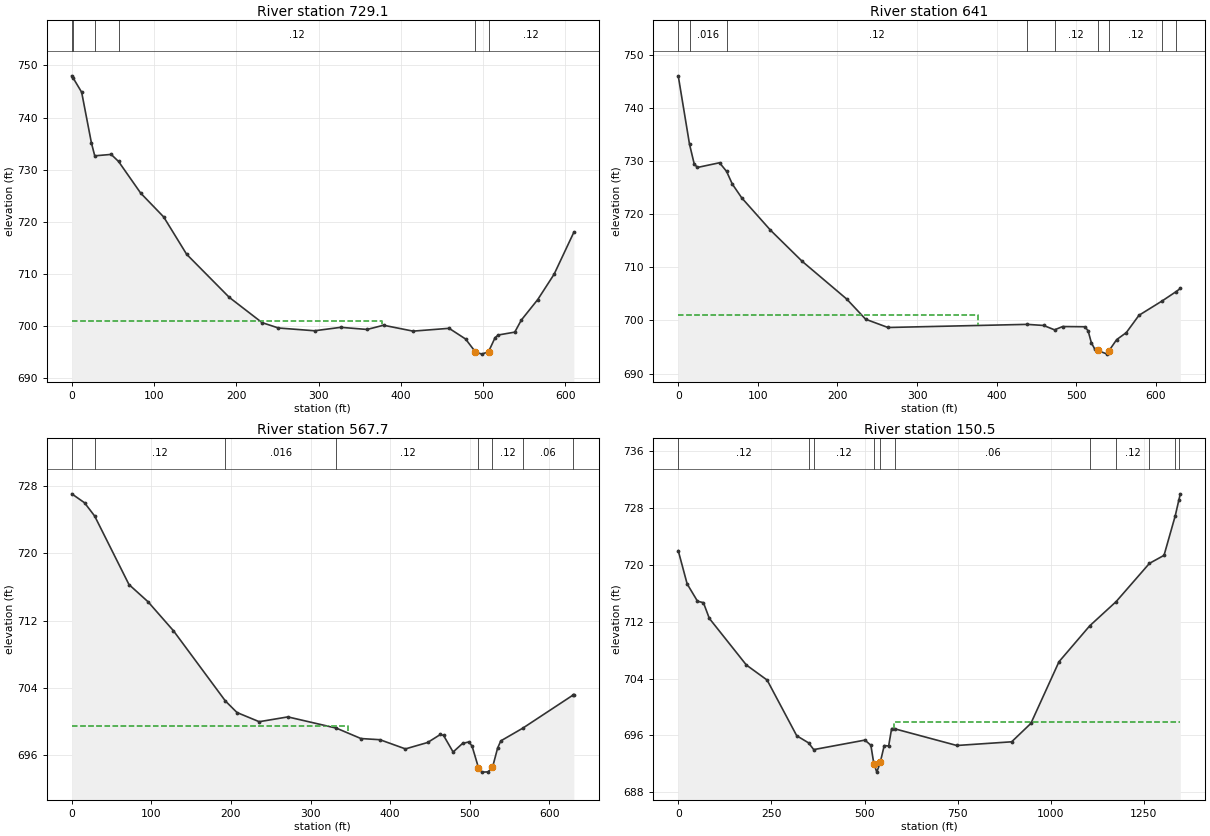
Type RM Length L Ch R = 1 ,729.1   ,88.7,88.2,87.7
XS GIS Cut Line= 2
     2315762.098      373778.521     2315556.699      373203.952
#Sta/Elev= 30
       0     748    1.35747.6727      12  744.86    23.9  735.12   27.92732.6601
    47.9  732.93   56.86731.5764    83.8   725.5   111.7  720.94   139.6  713.78
   191.4  705.52   231.3  700.67   251.2  699.64   295.1  699.11     327  699.77
   358.9  699.36   378.9  700.17   414.8  699.04   458.6  699.58   478.6  697.53
   490.5  695.07   498.3  694.63   506.5  695.09   514.5   697.8   518.4   698.3
   538.4  698.85   546.4  701.17   566.3  705.09   586.2  709.95   610.2     718
#Mann= 6 ,-1 , 0
       0    .016       0    1.35     .12       0   27.92    .016       0
   56.86     .12       0   490.5    .045       0   506.5     .12       0
#XS Ineff= 2 , 0
          377.09  700.95
Permanent Ineff=
       F       F
Bank Sta=490.5,506.5
XS Rating Curve= 0 ,0
Exp/Cntr=0.3,0.1

Type RM Length L Ch R = 1 ,641     ,73.2,73.2,73.2
XS GIS Cut Line= 2
     2315864.789      373768.537     2315639.105      373179.528
#Sta/Elev= 30
       0     746   14.17733.1317      20  729.47      24  728.76    51.9  729.65
   60.75728.0213    67.9  725.65    79.8  723.04   115.8  716.98   155.7  711.11
   211.6  704.02   235.5  700.21   263.5  698.66  438.46699.2491   459.1  699.04
  472.79698.2196     483  698.84     511   698.8     515  698.02     519  695.81
     523  694.68     527  694.34     539  693.65  541.12  694.28   550.9  696.39
   562.9  697.69   578.9  700.96  608.06703.6628  625.73705.4296   630.8     706
#Mann= 9 ,-1 , 0
       0     .12       0   14.17    .016       0   60.75     .12       0
  438.46    .016       0  472.79     .12       0     527    .045       0
  541.12     .12       0  608.06     .06       0  625.73     .12       0
#XS Ineff= 2 , 0
          377.09  701.05
Permanent Ineff=
       F       F
Bank Sta=527,541.12
XS Rating Curve= 0 ,0
Exp/Cntr=0.3,0.1

Type RM Length L Ch R = 1 ,567.7   ,407.7,417.2,426.6
XS GIS Cut Line= 2
     2315927.843      373728.818     2315702.159      373139.808
#Sta/Elev= 30
       0  727.05      16  725.99   28.71724.4207    71.9  716.27    95.8  714.23
   127.8  710.78  193.02702.4399   207.6  701.07   235.5  699.98   271.5  700.55
  332.55699.2122   363.3  697.98   387.2  697.84   419.2  696.75   447.1  697.51
   463.1  698.46   467.1  698.35   479.1  696.38     491   697.4     499  697.58
     503  697.06     511  694.51     515  693.99     523  694.02  528.59  694.55
     535  696.84     539   697.7   566.5 699.204  630.29703.1743   630.8  703.21
#Mann= 8 ,-1 , 0
       0    .016       0   28.71     .12       0  193.02    .016       0
  332.55     .12       0     511    .045       0  528.59     .12       0
   566.5     .06       0  630.29    .016       0
#XS Ineff= 2 , 0
          347.47  699.46
Permanent Ineff=
       F       F
Bank Sta=511,528.59
XS Rating Curve= 0 ,0
Exp/Cntr=0.3,0.1

Type RM Length L Ch R = 1 ,150.5   ,161.5,150.5,139.5
XS GIS Cut Line= 4
     2316036.078      373744.537     2316126.822      373532.537
     2316157.609      372932.532     2315645.256      372868.537
#Sta/Elev= 30
       0     722    23.9  717.32    51.7  714.88    67.6  714.68    83.5  712.46
   182.9   705.9   238.6  703.78   318.1  695.94  349.87 694.939  363.67693.9915
   501.2  695.33   517.1   694.6     525  692.02     533  690.82   542.2  692.18
   552.9  694.56   564.8   694.5   572.8  696.96  581.82696.9084   747.8  694.57
     895  695.09   946.6  697.68    1022  706.36 1104.63711.4225 1175.42714.8257
 1264.85 720.211    1304  721.34  1334.2 726.928 1344.03729.1813  1347.7     730
#Mann= 11 ,-1 , 0
       0     .12       0  349.87     .06       0  363.67     .12       0
     525    .045       0   542.2     .12       0  581.82     .06       0
 1104.63     .08       0 1175.42     .12       0 1264.85    .016       0
  1334.2     .06       0 1344.03    .016       0
#XS Ineff= 2 , 0
                          579.36          697.91
Permanent Ineff=
       F       F
Bank Sta=525,542.2
XS Rating Curve= 0 ,0
Exp/Cntr=0.3,0.1

Chan Stop Cuts=-1
Use User Specified Reach Order=0
Composite Channel Slope=5